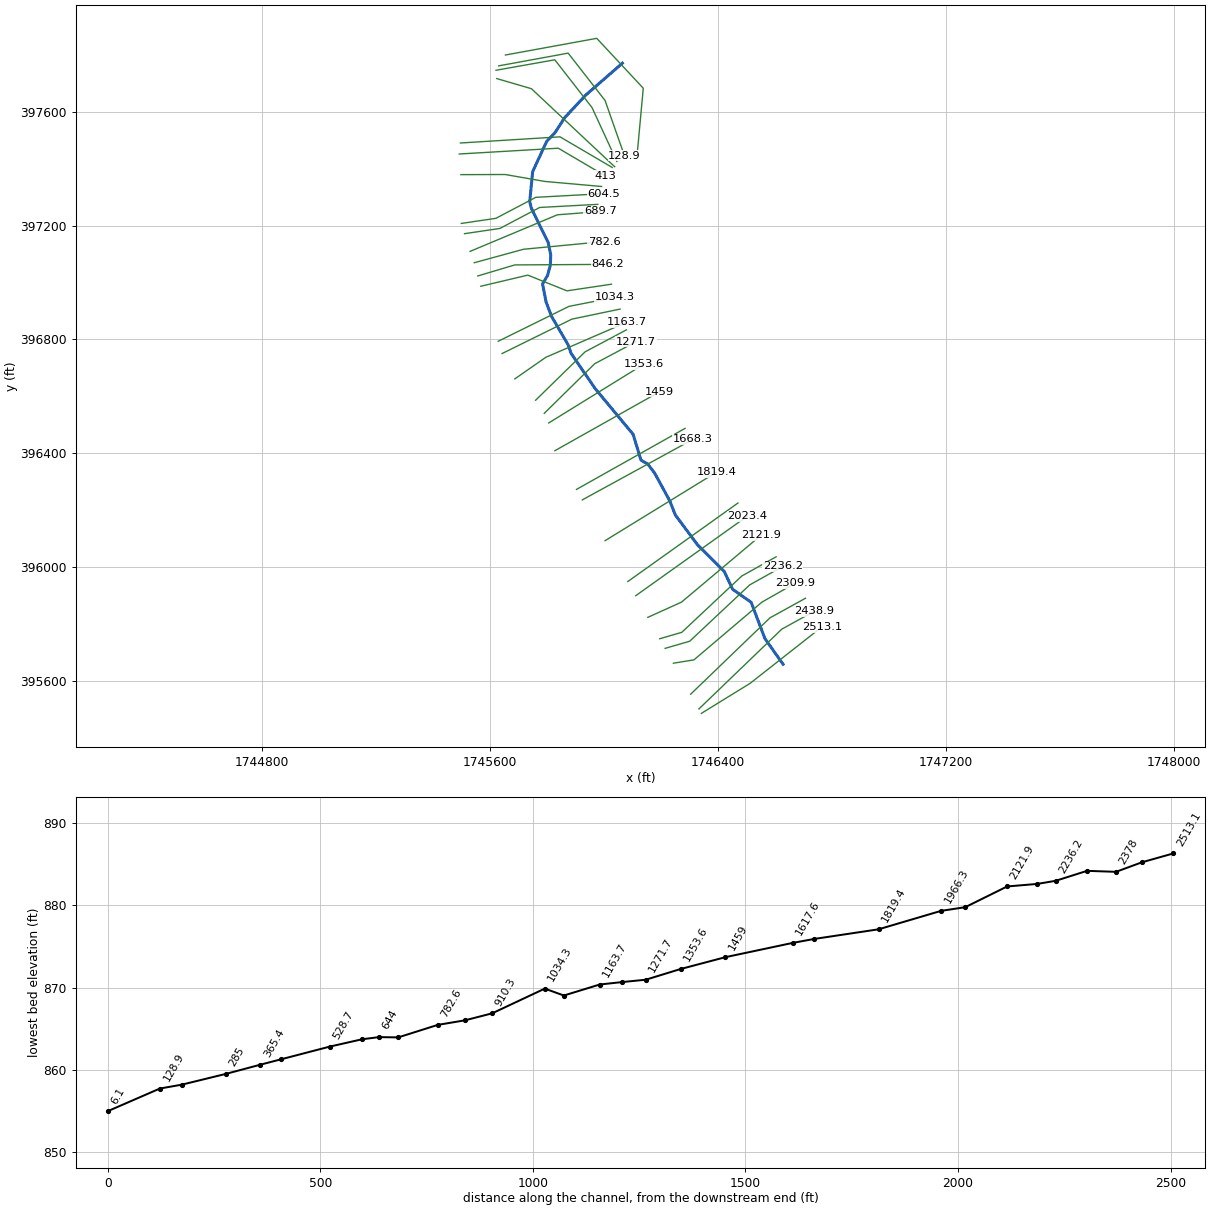
--- RFROCKCK.prj (project) ---

Proj Title=RFROCKCK
Current Plan=p01
Default Exp/Contr=0,0
English Units
Geom File=g01
Flow File=f01
Plan File=p01
BEGIN DESCRIPTION:
END DESCRIPTION:
DSS Export Rating Curves= 0
DSS Export Rating Curve Sorted= 0
DSS Export Volume Flow Curves= 0
DXF OffsetX= 0
DXF OffsetY= 0
DXF ScaleX= 0
DXF ScaleY= 0

--- RFROCKCK.p01 (plan) ---

Plan Title=Floodplain
Program Version=4.00
Geom File=g01
Flow File=f01
K Sum by GR=0
Std Step Tol=0.01
Critical Tol=0.01
Num of Std Step Trials=20
Max Error Tol=0.3
Flow Tol Ratio=0.001
Split Flow NTrial=30
Split Flow Tol=0.02
Split Flow Ratio=0.02
Log Output Level=0
Friction Slope Method=1
Unsteady Friction Slope Method=2
Unsteady Bridges Friction Slope Method=1
Global Log Level=0
CheckData=False
Run HTab=0
Run UNet=0
Run PostProcess=0
UNET Theta=0
UNET Theta Warmup=0
UNET ZTol=0
UNET ZSATol=0
UNET MxIter=0
UNET MaxInSteps=0
UNET DtIC=0
UNET DtMin=0
UNET MaxCRTS=0
UNET WFStab=0
UNET SFStab=0
UNET WFX=0
UNET SFX=0
UNET DSS MLevel=0
UNET DZMax Abort=0
UNET Convert EG Bridges=0
UNET Use Existing IB Tables=0
UNET Froude Limit=0
UNET Froude Power=0
Write IC File=0
Echo Input=False
Echo Output=False
Write Detailed=0

--- RFROCKCK.f01 (steady flow) ---

Flow Title=NFF Regression Equation
Program Version=4.00
Number of Profiles=1
Profile Names=P100yr
River Rch & RM=RFROCKCK,Main      ,2513.1
767.6497
River Rch & RM=RFROCKCK,Main      ,2378
767.8803
River Rch & RM=RFROCKCK,Main      ,2023.4
1047.097
River Rch & RM=RFROCKCK,Main      ,528.7
1099.460
River Rch & RM=RFROCKCK,Main      ,285
1113.277
Boundary for River Rch & Prof#=RFROCKCK,Main      ,1
Up Type=0
Dn Type=3
Dn Slope=0.014746

--- RFROCKCK.g01 (geometry) ---

Geom Title=USGS 10m DEM
Program Version=4.10

River Reach=RFROCKCK        ,Main
Reach XY= 30
     1746629.381      395657.965      1746565.81      395747.964
     1746517.436      395875.712      1746452.59      395921.446
     1746422.556      395984.927     1746329.723      396077.213
     1746251.225      396183.015     1746232.112      396232.162
     1746178.187      396331.138     1746154.297      396362.196
     1746131.089      396375.165     1746103.103      396466.633
      1745970.68      396626.359     1745885.355       396751.41
     1745875.799      396780.079     1745817.096      396881.103
     1745797.984      396931.615     1745785.697      396995.096
     1745802.762      397024.106     1745813.001      397060.283
     1745814.366      397097.143     1745805.492      397140.147
     1745746.107      397261.648     1745740.646      397284.856
     1745750.885      397389.634     1745800.031      397496.119
     1745829.383      397526.835     1745862.848      397578.999
     1745937.915      397659.599      1746065.56      397770.862

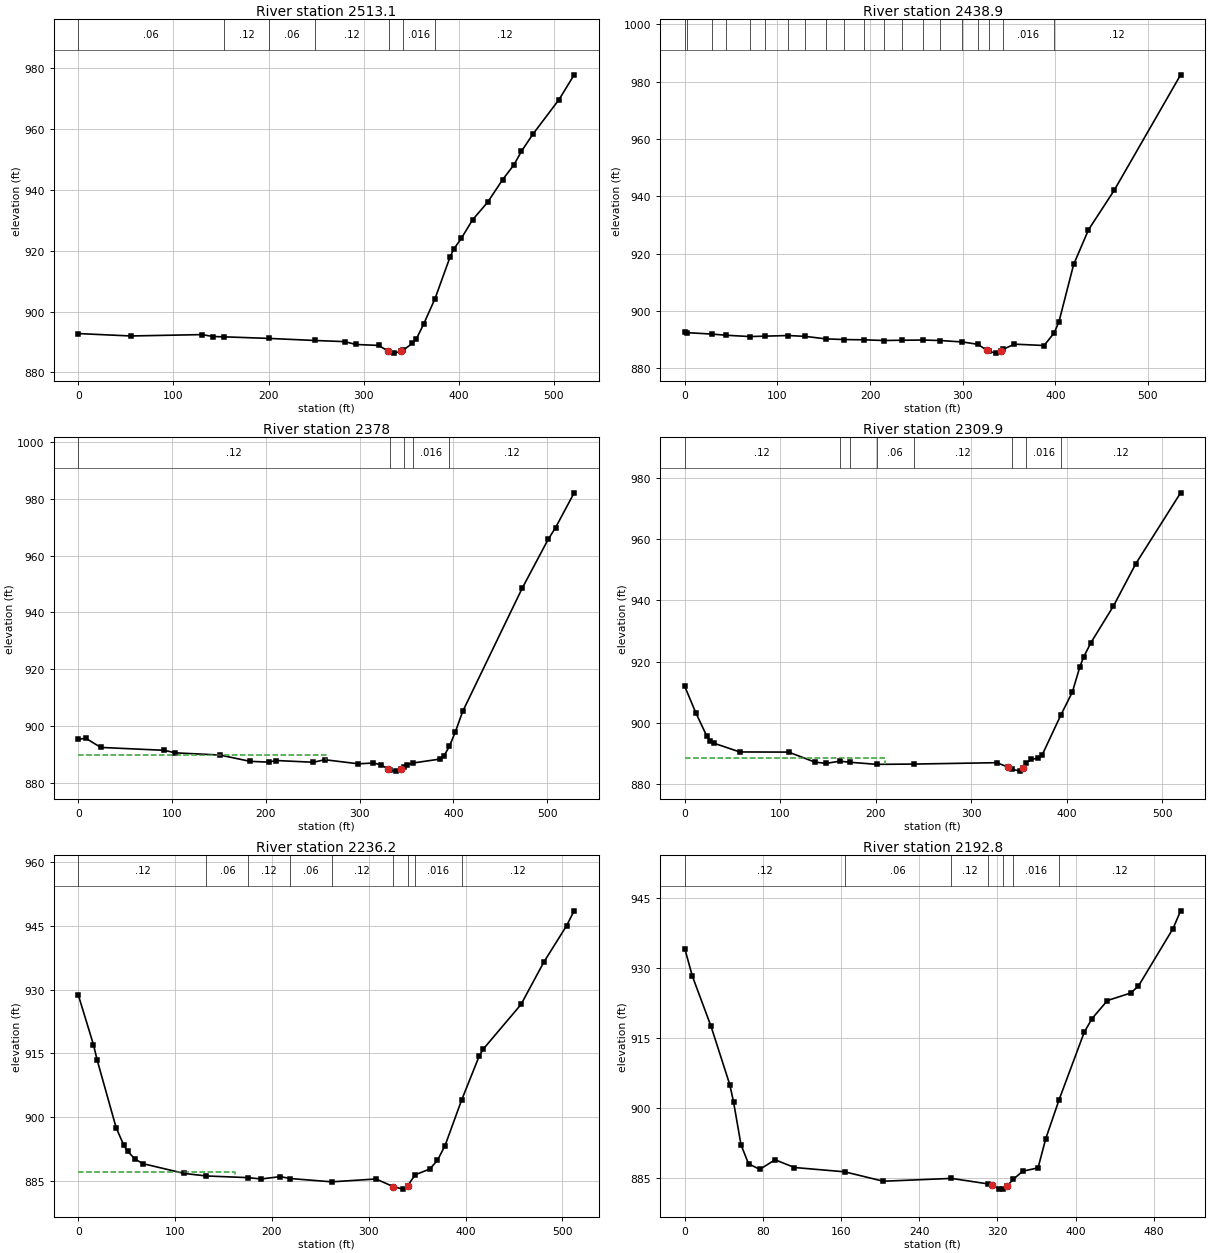
Type RM Length L Ch R = 1 ,2513.1  ,71.9,74.2,76.5
XS GIS Cut Line= 3
     1746342.777       395485.23     1746513.715      395590.766
       1746765.4      395789.004
#Sta/Elev= 30
       0  892.75    55.2  891.96     130  892.41   141.8  891.77  153.38891.6777
  200.92891.1499  248.65890.4768     280   890.1   291.9  889.16   315.6  888.86
  325.43  887.07   326.8  886.78   331.4  886.32   339.3  886.92   341.8  887.36
   351.2  889.52   355.2  890.84   363.1   895.9  375.01904.2297   390.8  917.91
   394.7  920.51   402.6  924.02   414.5  930.15   430.3  935.91   446.1  943.36
     458  948.23   465.9  952.68   477.8  958.25   505.4  969.68   521.3  977.81
#Mann= 7 ,-1 , 0
       0     .06       0  153.38     .12       0  200.92     .06       0
  248.65     .12       0   326.8    .045       0   341.8    .016       0
  375.01     .12       0
Bank Sta=325.43,339.3
XS Rating Curve= 0 ,0
Exp/Cntr=0.3,0.1

Type RM Length L Ch R = 1 ,2438.9  ,60.7,60.9,61.7
XS GIS Cut Line= 3
      1746334.14      395500.751     1746624.785      395781.257
     1746739.738      395844.863
#Sta/Elev= 30
       0  892.47    2.05892.3931   29.19891.8922   44.59891.4811   70.24891.0248
   87.12891.1724  111.28891.3828  129.65 891.098  152.33 890.215  172.18 889.975
  193.38  889.89  214.71889.6471  234.43889.7339  257.24889.8135  275.48889.6404
  299.77889.1357  316.52888.3108  326.04  886.23   328.3  885.84   335.9  885.24
  341.18  885.97   343.3  886.51   355.9  888.37   387.9   887.9  398.62892.2224
   403.9  896.14   419.8  916.19   435.8  928.27   463.6  942.08   535.3  982.38
#Mann= 20 ,-1 , 0
       0     .06       0    2.05    .016       0   29.19     .06       0
   44.59    .016       0   70.24     .06       0   87.12    .016       0
  111.28     .06       0  129.65    .016       0  152.33     .06       0
  172.18    .016       0  193.38     .06       0  214.71    .016       0
  234.43     .12       0  257.24    .016       0  275.48     .12       0
  299.77    .016       0  316.52     .12       0   328.3    .045       0
   343.3    .016       0  398.62     .12       0
Bank Sta=326.04,341.18
XS Rating Curve= 0 ,0
Exp/Cntr=0.3,0.1

Type RM Length L Ch R = 1 ,2378    ,68.7,68.1,65.5
XS GIS Cut Line= 3
     1746305.252      395552.666     1746583.119       395820.84
     1746707.905      395889.887
#Sta/Elev= 30
       0  895.28       8  895.66    23.9  892.43    91.6  891.41   103.5  890.52
   151.3  889.74   183.1  887.53     203  887.25     211  887.82   250.8   887.2
   262.8   888.1   298.6  886.66   314.5  886.93   322.5  886.36   330.4  884.82
   332.2  884.51   338.4  884.08  344.35  884.72   347.2  885.42   350.3  886.33
  356.67886.9278   386.2  888.35   390.1   889.5  395.67892.7855     402  897.82
   409.9   905.1   473.3  948.46     501  965.68     509  969.89   528.8  982.12
#Mann= 5 ,-1 , 0
       0     .12       0   332.2    .045       0   347.2     .12       0
  356.67    .016       0  395.67     .12       0
#XS Ineff= 2 , 0
          263.78  889.73
Permanent Ineff=
       F       F
Bank Sta=330.4,344.35
XS Rating Curve= 0 ,0
Exp/Cntr=0.3,0.1

Type RM Length L Ch R = 1 ,2309.9  ,73.4,73.7,75.7
XS GIS Cut Line= 4
      1746244.61      395661.646     1746316.626      395673.271
     1746555.341      395876.396     1746670.888      395942.242
#Sta/Elev= 30
       0  911.87    11.5   903.3      23  895.68    26.9  894.02    30.7  893.31
    57.6  890.47   108.7  890.42   136.4  887.14   148.3  886.74  162.31887.4561
  173.54887.0876  201.09886.4149  239.87886.5093   326.9  886.96   338.8  885.48
   342.8  884.86   350.7   884.2   354.6  885.35   357.8  886.85   362.6  888.02
   370.5  888.47   374.5  889.58  393.93902.5296     406  910.06   413.8  918.26
   417.7  921.45   425.5  926.24     449  938.16   472.4  951.99   519.4  975.19
#Mann= 8 ,-1 , 0
       0     .12       0  162.31     .06       0  173.54     .12       0
  201.09     .06       0  239.87     .12       0   342.8    .045       0
   357.8    .016       0  393.93     .12       0
#XS Ineff= 2 , 0
          209.29  888.61
Permanent Ineff=
       F       F
Bank Sta=338.8,354.6
XS Rating Curve= 0 ,0
Exp/Cntr=0.3,0.1

Type RM Length L Ch R = 1 ,2236.2  ,43,43.4,43.1
XS GIS Cut Line= 4
       1746215.6       395713.78     1746301.869      395738.896
     1746512.285      395936.813     1746628.607      396002.042
#Sta/Elev= 30
       0  928.74    15.6  917.06    19.5  913.38    39.1  897.43    46.9  893.38
    50.8  891.91    58.6  890.09    66.4  889.01   109.6  886.68  132.33886.0893
  175.43885.6989   188.8  885.38   208.6  885.94  218.54885.4954  261.65  884.71
   307.5  885.38     325   883.6   335.2  882.99     340  883.72  347.87886.3687
   362.9  887.72   370.8  889.75   378.7  893.22  395.88903.9976     414  914.34
     418  915.95   457.2  926.52   480.7  936.48   504.2  945.06   512.1   948.6
#Mann= 9 ,-1 , 0
       0     .12       0  132.33     .06       0  175.43     .12       0
  218.54     .06       0  261.65     .12       0     325    .045       0
     340     .12       0  347.87    .016       0  395.88     .12       0
#XS Ineff= 2 , 0
          161.61  886.98
Permanent Ineff=
       F       F
Bank Sta=325,340
XS Rating Curve= 0 ,0
Exp/Cntr=0.3,0.1

Type RM Length L Ch R = 1 ,2192.8  ,72.2,70.9,69.5
XS GIS Cut Line= 4
     1746196.763      395747.633     1746274.091      395770.146
     1746484.508      395968.063     1746604.899      396035.574
#Sta/Elev= 30
       0  934.09     7.7  928.24    26.8   917.5      46  905.01    49.9  901.26
    57.5  892.13    65.2  888.04    76.7  886.84    92.4   888.9   112.2  887.24
  163.62886.3177   203.2   884.3  272.91884.9077   310.6  883.72     314  883.51
   321.9  882.61   325.6  882.62   329.8  883.29  336.05884.6975   345.7  886.44
   361.5  887.16   369.4  893.43  383.07901.7773   408.8  916.23   416.7  919.12
   432.5     923   456.2   924.6   464.1  926.06   499.6   938.4   507.4  942.21
#Mann= 7 ,-1 , 0
       0     .12       0  163.62     .06       0  272.91     .12       0
   310.6    .045       0   325.6     .12       0  336.05    .016       0
  383.07     .12       0
Bank Sta=314,329.8
XS Rating Curve= 0 ,0
Exp/Cntr=0.3,0.1

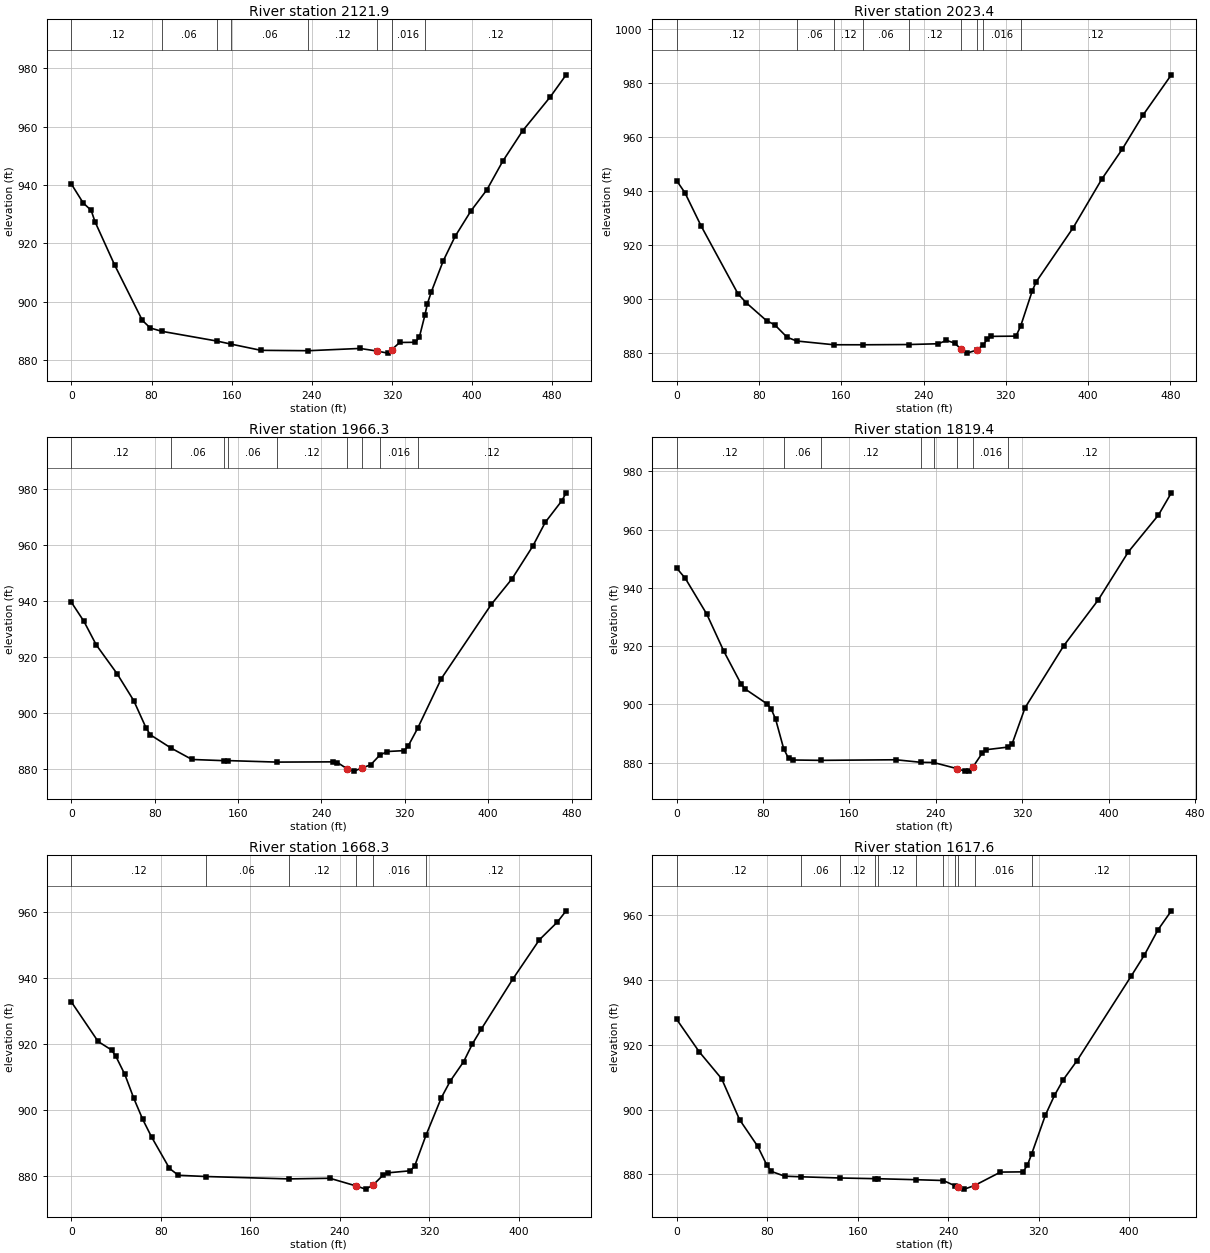
Type RM Length L Ch R = 1 ,2121.9  ,100.3,98.5,96.7
XS GIS Cut Line= 3
      1746154.94      395822.792     1746273.223      395876.396
     1746551.597      396110.962
#Sta/Elev= 30
       0  940.31    11.8  933.83    19.7  931.32    23.6  927.37    43.3  912.45
    70.8  893.56    78.7  890.94    90.1889.7969  144.98886.4618  159.75885.3691
   189.2  883.26  236.65883.1304   288.1  883.91   304.7  883.04   315.8   882.3
   319.7  883.43   327.7  885.96   343.5  886.02   347.5  887.93  352.87895.2742
   355.4  899.24   359.4  903.39   371.2  913.94   383.1  922.38   398.9  931.12
   414.8  938.36   430.6  948.14   450.4  958.56   478.1  970.25   493.9  977.82
#Mann= 8 ,-1 , 0
       0     .12       0    90.1     .06       0  144.98     .12       0
  159.75     .06       0  236.65     .12       0   304.7    .045       0
   319.7    .016       0  352.87     .12       0
Bank Sta=304.7,319.7
XS Rating Curve= 0 ,0
Exp/Cntr=0.3,0.1

Type RM Length L Ch R = 1 ,2023.4  ,57,57.1,57.1
XS GIS Cut Line= 2
     1746112.576      395898.925     1746503.891      396178.436
#Sta/Elev= 30
       0  943.79       8  939.34    23.8  926.97    59.6  901.82    67.6  898.49
    87.4  891.82    95.4  890.28   107.3  885.69  116.62884.2822  152.92882.8856
  181.26 882.877  225.51882.9695   254.4  883.26   262.3   884.5   270.2  883.51
   276.5  881.28   282.2  879.78   291.5  880.88   298.1  882.87     302  884.95
     306     886   329.9  886.09   334.4 889.794   345.8  903.01   349.7  906.34
   385.5  926.34   413.3  944.36   433.2  955.48   453.1  967.97   480.9  983.06
#Mann= 9 ,-1 , 0
       0     .12       0  116.62     .06       0  152.92     .12       0
  181.26     .06       0  225.51     .12       0   276.5    .045       0
   291.5     .12       0   298.1    .016       0   334.4     .12       0
Bank Sta=276.5,291.5
XS Rating Curve= 0 ,0
Exp/Cntr=0.3,0.1

Type RM Length L Ch R = 1 ,1966.3  ,148.2,146.9,145.1
XS GIS Cut Line= 2
     1746084.825      395948.795     1746471.151      396224.743
#Sta/Elev= 30
       0   939.6      12  932.82    23.9  924.37    43.9  914.08    59.8  904.52
    71.8  894.65    75.8  892.29   95.47887.6035   115.7  883.49  146.28883.0666
  150.72883.0834  197.09882.5559   251.3  882.64   255.3  882.41   264.2  880.26
   271.3  879.33   279.2  880.52   287.2  881.57  295.91885.0101   303.2  886.33
   319.2  886.65   323.2  888.28  332.21894.5502   355.1   912.4     403  938.86
   422.9     948   442.8  959.64   454.8  968.16   470.8  975.91   474.8  978.69
#Mann= 9 ,-1 , 0
       0     .12       0   95.47     .06       0  146.28     .12       0
  150.72     .06       0  197.09     .12       0   264.2    .045       0
   279.2     .12       0  295.91    .016       0  332.21     .12       0
Bank Sta=264.2,279.2
XS Rating Curve= 0 ,0
Exp/Cntr=0.3,0.1

Type RM Length L Ch R = 1 ,1819.4  ,153.6,151.1,150
XS GIS Cut Line= 2
     1746004.917      396092.398     1746394.945      396332.526
#Sta/Elev= 30
       0  946.78       8  943.27    27.9  930.98    43.8  918.16    59.7  906.97
    63.7  905.21    83.6   900.2    87.6  898.37    91.6  894.96   99.13884.7592
   103.6  881.48   107.5  880.91  133.82  880.79   203.1  880.99  226.28880.1084
  237.87880.0543   259.2  877.98   266.8  877.09   270.8  877.21   274.2  878.46
   282.8   883.2   286.8  884.45  307.24885.3576   310.7  886.56   322.6  898.86
   358.4  920.14   390.3  935.83   418.2  952.34   446.1     965     458  972.61
#Mann= 8 ,-1 , 0
       0     .12       0   99.13     .06       0  133.82     .12       0
  226.28     .06       0  237.87     .12       0   259.2    .045       0
   274.2    .016       0  307.24     .12       0
Bank Sta=259.2,274.2
XS Rating Curve= 0 ,0
Exp/Cntr=0.3,0.1

Type RM Length L Ch R = 1 ,1668.3  ,49.9,50.6,49.4
XS GIS Cut Line= 2
     1745925.134      396235.777     1746312.966      396448.474
#Sta/Elev= 30
       0  932.65    23.9  920.67    35.9  918.09    39.8  916.14    47.8  910.67
    55.8  903.43    63.8  897.04    71.7  891.71    87.7   882.2    95.6  880.12
   119.9879.7462  194.23879.0186   231.1  879.21   254.3  876.91     263  875.92
   269.3  877.04     279  880.27   282.9  880.86   302.9  881.48   306.8  882.82
  317.07892.2836   330.8  903.66   338.7  908.67   350.7  914.56   358.6  919.99
   366.6   924.5   394.5  939.52   418.4   951.5   434.4  956.84   442.3  960.28
#Mann= 6 ,-1 , 0
       0     .12       0   119.9     .06       0  194.23     .12       0
   254.3    .045       0   269.3    .016       0  317.07     .12       0
Bank Sta=254.3,269.3
XS Rating Curve= 0 ,0
Exp/Cntr=0.3,0.1

Type RM Length L Ch R = 1 ,1617.6  ,158.6,158.6,158.3
XS GIS Cut Line= 2
     1745904.665      396272.562     1746285.596      396487.185
#Sta/Elev= 30
       0  927.87    19.9  917.86    39.8  909.51    55.6   896.9    71.6  888.68
    79.5  883.02    83.5  880.94    95.4  879.44  110.26879.2434  144.17 878.882
  175.51878.6669  178.07878.6542  211.97878.3463  235.67878.1015  245.87876.4941
   248.3   876.1   254.4  875.44   263.3  876.56   286.2   880.7   306.1  880.77
     310  882.83  313.67886.2156   325.9  898.29   333.9  904.36   341.8  909.27
   353.8  915.07   401.5  941.09   413.4  947.72   425.3  955.44   437.2  961.36
#Mann= 11 ,-1 , 0
       0     .12       0  110.26     .06       0  144.17     .12       0
  175.51     .06       0  178.07     .12       0  211.97    .016       0
  235.67     .12       0  245.87    .016       0   248.3    .045       0
   263.3    .016       0  313.67     .12       0
Bank Sta=248.3,263.3
XS Rating Curve= 0 ,0
Exp/Cntr=0.3,0.1

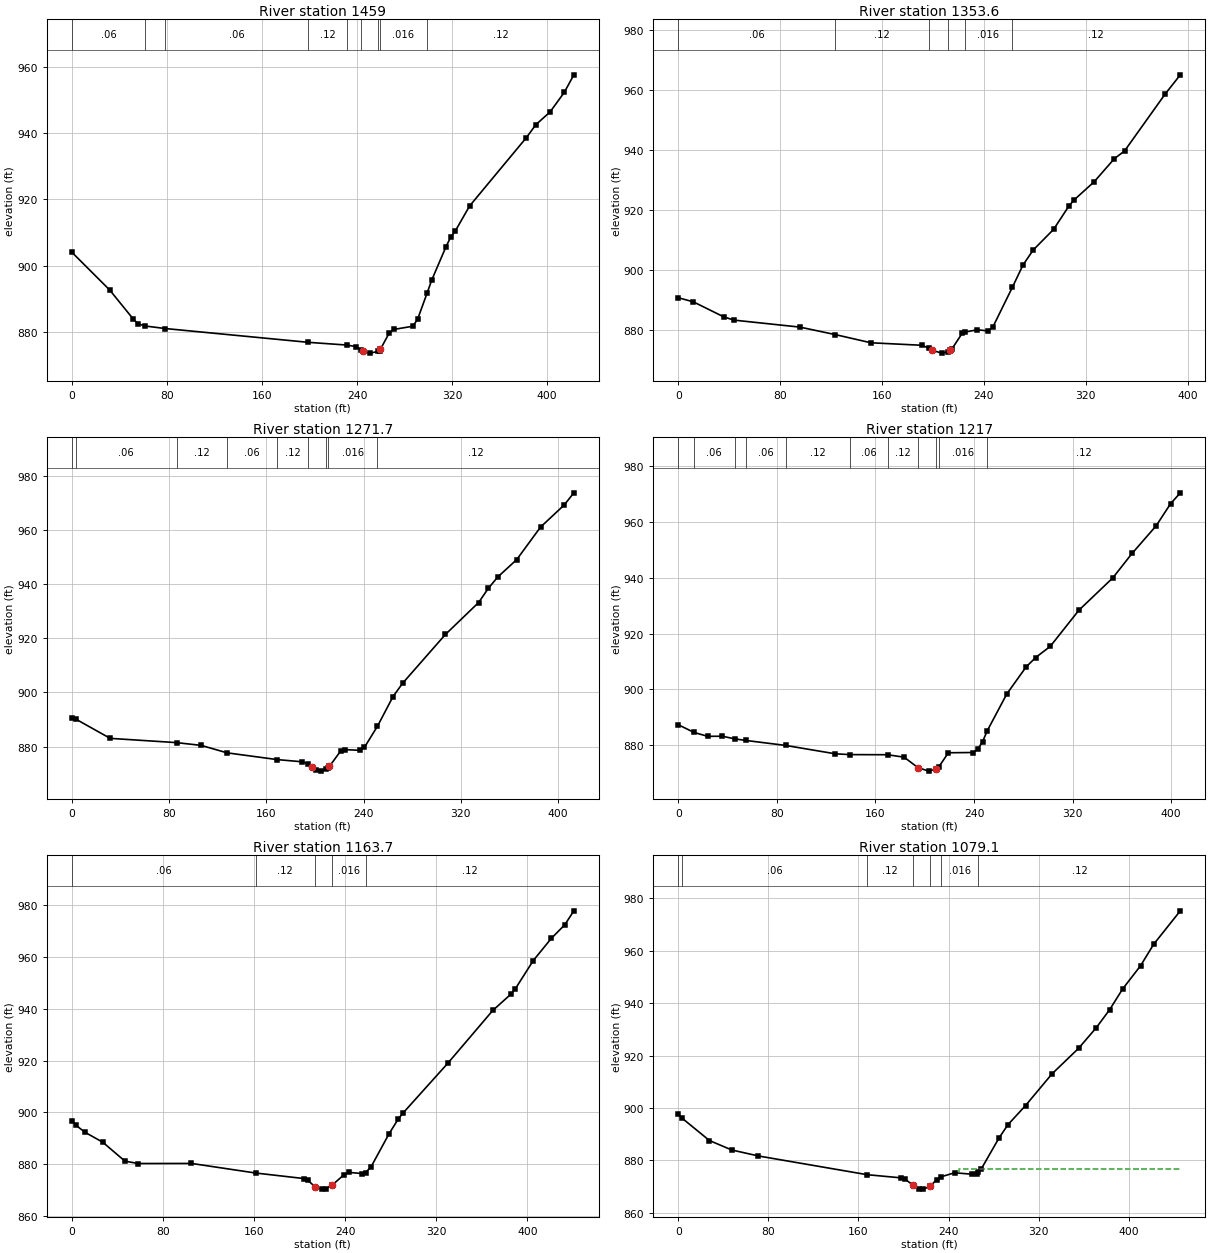
Type RM Length L Ch R = 1 ,1459    ,104.7,105.4,106.6
XS GIS Cut Line= 2
     1745828.921      396408.681     1746196.824      396616.116
#Sta/Elev= 30
       0  904.11    31.9  892.72    51.8  883.93    55.8  882.51   61.61881.8759
   78.67881.1058  198.94876.9532  231.15876.1379   239.1  875.67     243  874.74
  244.87  874.42     251   873.7     258  874.23  259.08874.4422  259.68  874.86
     267  879.72   270.9  880.83   286.9   881.8   290.9  883.86  298.96891.8012
   302.8  895.67   314.8  905.72   318.8  908.64   322.7  910.51   334.7  918.02
   382.5  938.62   390.5  942.53   402.4  946.34   414.4  952.26   422.4  957.52
#Mann= 9 ,-1 , 0
       0     .06       0   61.61     .12       0   78.67     .06       0
  198.94     .12       0  231.15     .06       0     243    .045       0
     258     .06       0  259.08    .016       0  298.96     .12       0
Bank Sta=244.87,259.68
XS Rating Curve= 0 ,0
Exp/Cntr=0.3,0.1

Type RM Length L Ch R = 1 ,1353.6  ,76.8,81.9,87.1
XS GIS Cut Line= 2
     1745807.283      396506.235     1746142.353      396713.701
#Sta/Elev= 30
       0  890.75    11.9  889.36    35.8  884.34    43.8  883.27    95.5  880.94
  123.32 878.437   151.3  875.71   191.1  874.88   196.7  873.93     199  873.23
     207  872.26   211.7  872.74  213.21   873.2     215  873.77   222.9  878.89
  224.72 879.254   234.9  880.06   242.8  879.67   246.8  880.83  262.27894.2153
   270.7  901.72   278.7   906.7   294.6  913.52   306.5  921.23   310.5  923.28
   326.4  929.39   342.4  937.16   350.3  939.69   382.2  958.69   394.1   965.1
#Mann= 6 ,-1 , 0
       0     .06       0  123.32     .12       0   196.7    .045       0
   211.7     .12       0  224.72    .016       0  262.27     .12       0
Bank Sta=199,213.21
XS Rating Curve= 0 ,0
Exp/Cntr=0.3,0.1

Type RM Length L Ch R = 1 ,1271.7  ,54.8,54.7,54.5
XS GIS Cut Line= 3
     1745791.658       396540.09     1745968.742      396714.569
     1746113.707      396791.826
#Sta/Elev= 30
       0  890.53    3.27890.1785    31.6  883.06    86.2881.4861   106.5  880.46
  127.66877.7166  169.12875.2087   189.4  874.41   194.3  873.74   197.3  872.66
   201.2  871.41   205.2  870.96   209.3  871.74  210.59872.2492  211.95  872.74
     221  878.31   224.9  878.89   236.8  878.65   240.7  879.75  251.39887.5349
   264.2  898.49   272.1  903.42   307.3  921.44   334.6  933.23   342.5  938.41
   350.3  942.64   365.9  949.06   385.5  961.07     405  969.25   412.9  973.73
#Mann= 9 ,-1 , 0
       0     .12       0    3.27     .06       0    86.2     .12       0
  127.66     .06       0  169.12     .12       0   194.3    .045       0
   209.3     .12       0  210.59    .016       0  251.39     .12       0
Bank Sta=197.3,211.95
XS Rating Curve= 0 ,0
Exp/Cntr=0.3,0.1

Type RM Length L Ch R = 1 ,1217    ,61.6,53.3,45
XS GIS Cut Line= 3
     1745761.276      396586.096     1745934.887      396756.235
     1746079.853      396833.492
#Sta/Elev= 30
       0  887.34   12.72884.5754    23.9  883.17    35.9   883.2    45.8 882.255
   54.92881.6888   87.15879.8983   127.5  876.89  139.31876.6086  169.86876.5616
   183.3  875.68   194.4  871.97   203.2  870.68   209.4  871.48  211.22 872.064
   219.2  877.27   239.1  877.36   243.1  878.57     247  881.31  250.76885.1761
   266.6  898.37   282.2  908.02     290  911.44   301.8  915.41   325.2  928.46
   352.6  940.01   368.2  948.77   387.8  958.71   399.5  966.64   407.4  970.54
#Mann= 11 ,-1 , 0
       0     .12       0   12.72     .06       0    45.8     .12       0
   54.92     .06       0   87.15     .12       0  139.31     .06       0
  169.86     .12       0   194.4    .045       0   209.4     .12       0
  211.22    .016       0  250.76     .12       0
Bank Sta=194.4,209.4
XS Rating Curve= 0 ,0
Exp/Cntr=0.3,0.1

Type RM Length L Ch R = 1 ,1163.7  ,83.4,84.5,85.6
XS GIS Cut Line= 3
      1745688.41      396661.194     1745796.921      396736.899
     1746079.859      396859.792
#Sta/Elev= 30
       0  896.86     3.9  894.96    11.7  892.31    27.2   888.5    46.7  881.18
    58.4  880.27   105.1   880.3  161.32876.6074   203.5  874.48   207.4  873.75
   213.6  871.26   219.3  870.38   223.3  870.59   228.6  871.94   239.1  875.97
     243  876.86   254.9   876.4  257.92876.7473   262.8  879.02   278.6  891.78
   286.6  897.43   290.5   899.6     330  918.92   369.6  939.37   385.4  945.62
   389.4  947.73   405.2  958.67     421   967.2   432.9   972.5   440.8  977.86
#Mann= 5 ,-1 , 0
       0     .06       0  161.32     .12       0   213.6    .045       0
   228.6    .016       0  257.92     .12       0
Bank Sta=213.6,228.6
XS Rating Curve= 0 ,0
Exp/Cntr=0.3,0.1

Type RM Length L Ch R = 1 ,1079.1  ,44.8,44.8,44.8
XS GIS Cut Line= 3
     1745643.657      396750.218     1745888.348      396871.158
      1746057.43       396906.52
#Sta/Elev= 30
       0  897.66    2.96896.2688    27.7  887.58    47.5  883.98    71.2  881.69
  167.69874.5507   197.8  873.34   201.7  872.75   208.5  870.51   213.6  869.19
   217.6  869.04   223.5  870.06   229.4  872.68  233.59873.7756   245.3  875.28
   261.1  874.72     265  874.92  266.53875.6161     269  876.74   284.7  888.51
   292.6  893.58   308.3  900.93   331.8  913.02   355.4  922.77   371.1  930.63
   382.9  937.47   394.6  945.48   410.4  954.27   422.1   962.5   445.7  975.23
#Mann= 7 ,-1 , 0
       0    .016       0    2.96     .06       0  167.69     .12       0
   208.5    .045       0   223.5     .12       0  233.59    .016       0
  266.53     .12       0
#XS Ineff= 2 , 0
                          249.23          876.82
Permanent Ineff=
       F       F
Bank Sta=208.5,223.5
XS Rating Curve= 0 ,0
Exp/Cntr=0.3,0.1

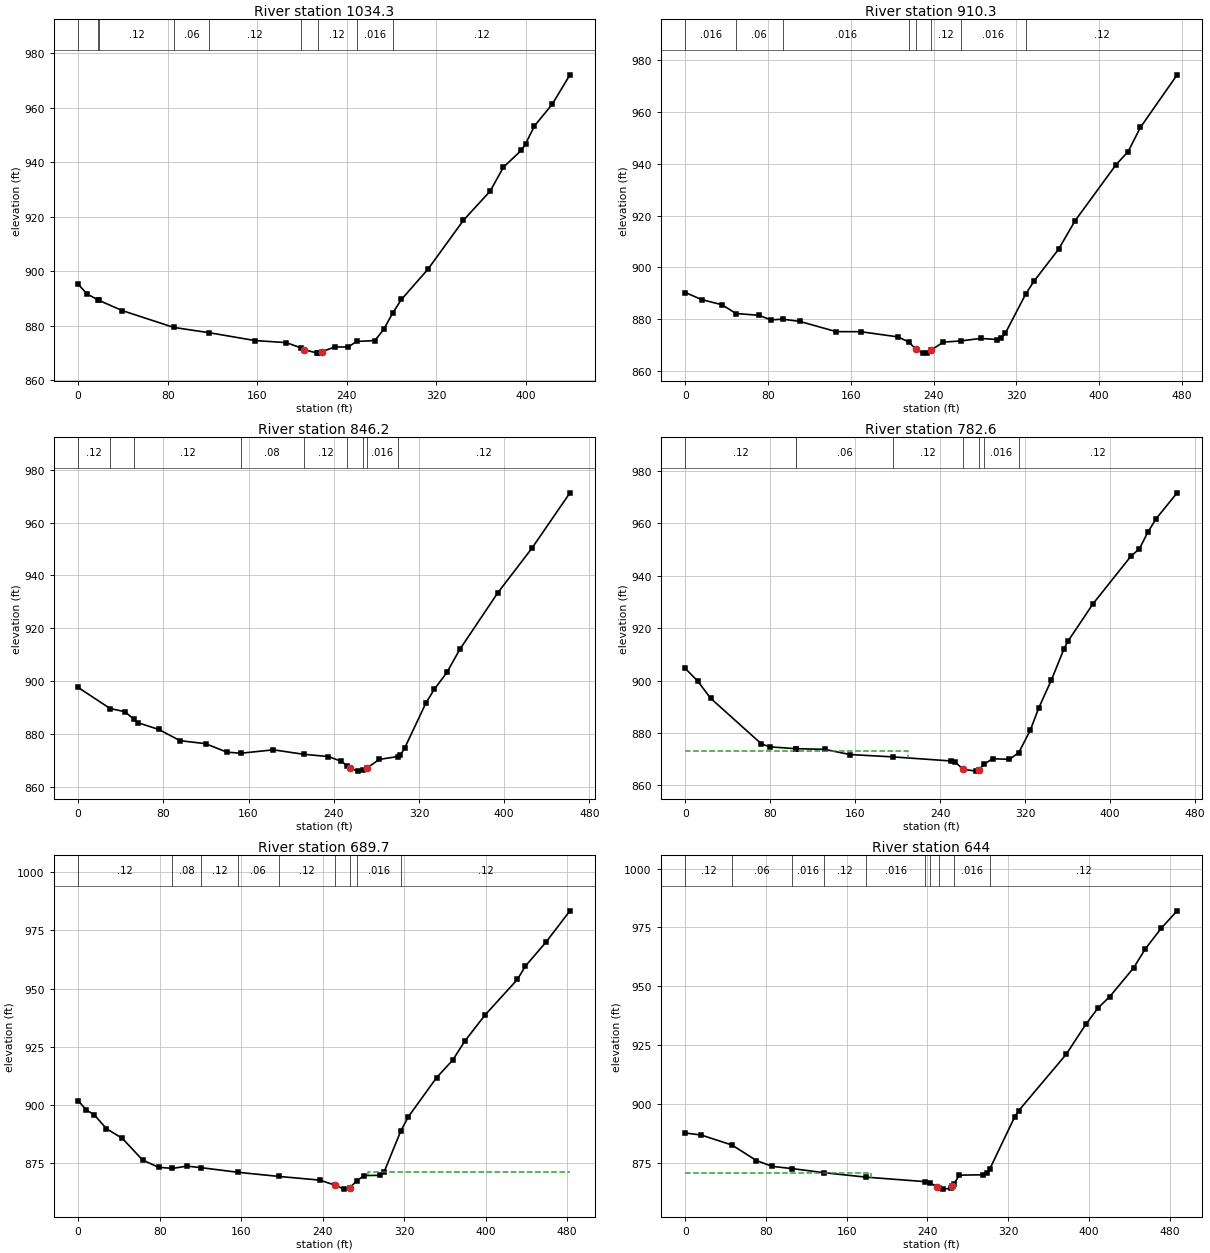
Type RM Length L Ch R = 1 ,1034.3  ,143.4,124,104.6
XS GIS Cut Line= 3
     1745630.159       396793.41     1745878.376      396916.091
     1746037.763      396947.492
#Sta/Elev= 30
       0  895.17     7.9  891.62   18.02889.3516   18.83889.1916    39.6  885.46
   85.48879.3059  116.86877.3836   158.2  874.48   185.9  873.74   199.4  871.74
   201.7  871.19   213.6  869.88   214.4  869.99   217.6  870.41   229.4  872.14
   241.3  872.14  248.64874.1578     265  874.48   272.9  878.58  281.18884.7274
   288.8  889.58   312.5  900.69   344.2  918.65     368  929.31   379.9  938.11
   395.8  944.28   399.7   946.7   407.6  953.25   423.5  961.22   439.3     972
#Mann= 9 ,-1 , 0
       0    .016       0   18.02     .06       0   18.83     .12       0
   85.48     .06       0  116.86     .12       0   199.4    .045       0
   214.4     .12       0  248.64    .016       0  281.18     .12       0
Bank Sta=201.7,217.6
XS Rating Curve= 0 ,0
Exp/Cntr=0.3,0.1

Type RM Length L Ch R = 1 ,910.3   ,55.3,64.2,72.9
XS GIS Cut Line= 4
     1745569.074      396986.849     1745734.005      397025.911
      1745871.14      396970.667     1746027.502      396994.045
#Sta/Elev= 30
       0  890.27    15.8  887.54    35.5  885.54   49.03882.1616      71  881.48
    82.8  879.69   93.94879.9837   110.4  879.14   145.8  875.17   169.5  875.14
   205.5  873.14  216.09871.1792   222.8  868.37   229.4  866.87   233.4  867.01
   237.8  868.09   249.4  871.12  266.01 871.563   285.4  872.54   301.4  872.13
   305.4  872.77   309.4   874.6  328.93889.6033   337.1  894.69   360.8  906.97
   376.6  917.89   416.2  939.55     428  944.67   439.9  954.02   475.4  974.32
#Mann= 8 ,-1 , 0
       0    .016       0   49.03     .06       0   93.94    .016       0
  216.09     .12       0   222.8    .045       0   237.8     .12       0
  266.01    .016       0  328.93     .12       0
Bank Sta=222.8,237.8
XS Rating Curve= 0 ,0
Exp/Cntr=0.3,0.1

Type RM Length L Ch R = 1 ,846.2   ,61.6,63.5,65.6
XS GIS Cut Line= 3
     1745558.411      397023.004     1745688.327      397061.813
     1746014.483      397063.738
#Sta/Elev= 30
       0  897.65   30.09889.6751    43.9  888.48   52.52885.5754    55.8  884.37
    75.8  881.76    95.7  877.53   119.6   876.4   139.6   873.2  152.65872.7815
   183.3  874.07  211.72872.3926     235  871.52     247  869.77   252.8  867.97
   254.9  867.16   262.9  866.02   267.8  866.54  270.79867.1081   282.8  870.45
  300.33871.5487   302.6  872.09   306.6  874.73   326.5  891.72   334.5     897
   346.4  903.42   358.3     912   394.1  933.47     426  950.23   461.8  971.22
#Mann= 9 ,-1 , 0
       0     .12       0   30.09    .016       0   52.52     .12       0
  152.65     .08       0  211.72     .12       0   252.8    .045       0
   267.8     .12       0  270.79    .016       0  300.33     .12       0
Bank Sta=254.9,270.79
XS Rating Curve= 0 ,0
Exp/Cntr=0.3,0.1

Type RM Length L Ch R = 1 ,782.6   ,86.1,93,99.8
XS GIS Cut Line= 3
     1745546.124       397069.49     1745718.655      397116.834
     1746001.513      397143.998
#Sta/Elev= 30
       0  904.63    11.9  899.69    23.8  893.27    71.6  875.87    79.5  874.73
   103.9874.0275  104.36874.0344   131.2  873.77     155   871.8  195.25870.9031
     250  869.35   253.9  868.92   261.7  866.17   273.6  865.47   276.7  866.08
  281.48868.1801   289.4   870.2   305.2  869.96  313.94872.5098   324.9  881.12
   332.8  889.58   344.7  900.22   356.5  912.03   360.4  915.08   384.1  929.39
   419.6  947.45   427.6  950.26   435.4  956.51   443.3  961.73   463.1  971.61
#Mann= 8 ,-1 , 0
       0     .12       0   103.9     .08       0  104.36     .06       0
  195.25     .12       0   261.7    .045       0   276.7     .12       0
  281.48    .016       0  313.94     .12       0
#XS Ineff= 2 , 0
          210.01  872.97
Permanent Ineff=
       F       F
Bank Sta=261.7,276.7
XS Rating Curve= 0 ,0
Exp/Cntr=0.3,0.1

Type RM Length L Ch R = 1 ,689.7   ,43.7,45.7,47.7
XS GIS Cut Line= 3
     1745531.409       397109.41     1745837.502      397237.984
     1745987.818      397249.622
#Sta/Elev= 30
       0  901.97     7.9  897.94    15.8  895.87    27.7  889.93    43.5   885.7
    63.2  876.46      79  873.33    92.6872.8335   106.7  873.82  120.76873.1648
  156.67871.1851  197.03869.4009   237.1  867.82   251.7  865.73   260.9  863.95
   266.7  864.62  273.29867.3589   280.6  869.79   296.4  869.86   300.4  871.38
  316.85  889.03   324.1  894.97   351.8  911.78   367.7  919.33   379.6  927.48
   399.4  938.66   431.2  953.95   439.1   959.7     459  969.81   482.8   983.4
#Mann= 9 ,-1 , 0
       0     .12       0    92.6     .08       0  120.76     .12       0
  156.67     .06       0  197.03     .12       0   251.7    .045       0
   266.7     .08       0  273.29    .016       0  316.85     .12       0
#XS Ineff= 2 , 0
                          284.31          871.35
Permanent Ineff=
       F       F
Bank Sta=251.7,266.7
XS Rating Curve= 0 ,0
Exp/Cntr=0.3,0.1

Type RM Length L Ch R = 1 ,644     ,39.8,39.4,39.5
XS GIS Cut Line= 4
     1745511.955      397171.663     1745635.897      397190.024
     1745775.653      397263.809     1745979.413      397274.739
#Sta/Elev= 30
       0   887.8    15.7  886.94   46.26882.6852    70.5   876.1    86.1  873.63
  105.97 872.683  137.08870.9672  179.32869.0557  237.28867.1747  242.58866.5776
  249.64  864.94   251.1  864.58   255.7  863.98   263.6  864.33  264.75   865.1
   266.1  866.04   271.5  869.91   295.1  870.06     299  870.81   301.7872.5043
   326.5  894.71   330.4  897.28   377.5   921.2   397.1  934.01   408.9  940.77
   420.7  945.68   444.2  957.81     456  965.98   471.7  974.69   487.4  982.05
#Mann= 10 ,-1 , 0
       0     .12       0   46.26     .06       0  105.97    .016       0
  137.08     .12       0  179.32    .016       0  237.28     .12       0
  242.58    .016       0   251.1    .045       0   266.1    .016       0
   301.7     .12       0
#XS Ineff= 2 , 0
          184.21  870.64
Permanent Ineff=
       F       F
Bank Sta=249.64,264.75
XS Rating Curve= 0 ,0
Exp/Cntr=0.3,0.1

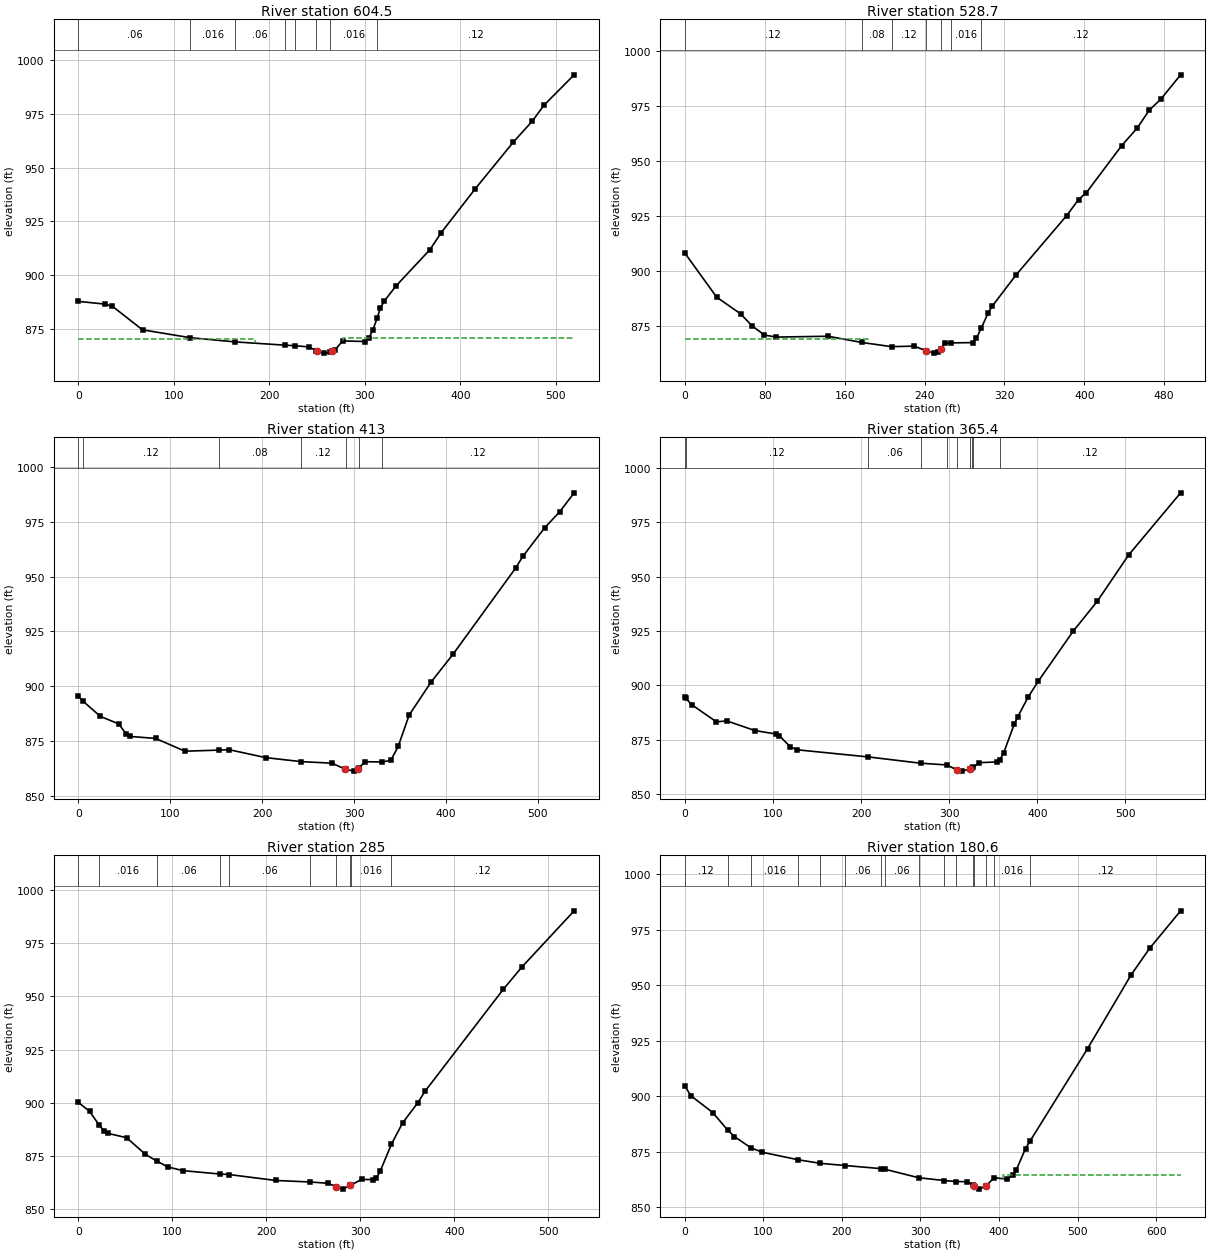
Type RM Length L Ch R = 1 ,604.5   ,90.6,75.9,60.5
XS GIS Cut Line= 4
     1745500.711      397207.645     1745622.008      397225.615
     1745761.765      397299.399     1745999.951      397312.391
#Sta/Elev= 30
       0  887.78    27.7  886.51    35.6  885.53    67.2  874.54  117.34 870.884
  163.68868.9565  216.91867.4064  226.94867.1621   241.2  866.61   248.9  864.93
  250.31864.6274     257  863.72   263.9  864.08  266.07  864.51   268.8  865.18
   276.7  869.41   300.5  869.12   304.5  870.98   308.5  874.55  312.94880.0735
   316.4  884.82   320.4   887.9   332.3  894.78   368.1  911.77     380  919.73
   415.8   940.2   455.6  961.85   475.5  971.62   487.4  978.87   519.2  993.08
#Mann= 8 ,-1 , 0
       0     .06       0  117.34    .016       0  163.68     .06       0
  216.91    .016       0  226.94     .12       0   248.9    .045       0
   263.9    .016       0  312.94     .12       0
#XS Ineff= 2 , 0
          184.52  870.41   277.4          870.88
Permanent Ineff=
       F       F
Bank Sta=250.31,266.07
XS Rating Curve= 0 ,0
Exp/Cntr=0.3,0.1

Type RM Length L Ch R = 1 ,528.7   ,109.3,115.7,121.3
XS GIS Cut Line= 4
     1745499.196       397379.21     1745654.578      397379.644
     1745793.033      397355.338     1745992.667      397337.594
#Sta/Elev= 30
       0  908.31    31.9  888.26    55.8   880.7    67.7  875.07    79.7  871.06
    91.6  870.12   143.4   870.5  176.99867.6938  206.98 865.771   229.6  866.01
   241.2     864   249.1  862.83     253  863.27   256.2  864.93   260.8  867.26
  266.95867.4727   288.2  867.61     292  869.59  296.93874.3134   303.8  881.17
   307.7  884.11   331.3  898.17   382.4  925.35   394.2  932.59   402.1  935.76
   437.4  957.11   453.2  965.21   464.9  973.15   476.7  978.28   496.4  989.26
#Mann= 7 ,-1 , 0
       0     .12       0  176.99     .08       0  206.98     .12       0
   241.2    .045       0   256.2     .12       0  266.95    .016       0
  296.93     .12       0
#XS Ineff= 2 , 0
          183.18  869.22
Permanent Ineff=
       F       F
Bank Sta=241.2,256.2
XS Rating Curve= 0 ,0
Exp/Cntr=0.3,0.1

Type RM Length L Ch R = 1 ,413     ,43.1,47.6,52.8
XS GIS Cut Line= 3
     1745493.379      397451.758     1745840.758      397472.142
     1746005.688       397374.92
#Sta/Elev= 30
       0  895.49    5.28 893.122      24  886.24      44  882.81      52  878.21
      56  877.11      84   876.2     116  870.37  153.21870.8593     164  871.06
     204  867.42  241.97865.6261     276  864.89  289.64   862.3   290.7  862.07
     300  861.27  304.75  862.44   305.7  862.91     312  865.56  330.73865.4581
     340  866.22     348  872.57   359.9  886.87   383.9  902.01   407.8  914.71
   475.6  953.87   483.6  959.29   507.5  972.43   523.5  979.54   539.4  988.28
#Mann= 7 ,-1 , 0
       0    .016       0    5.28     .12       0  153.21     .08       0
  241.97     .12       0   290.7    .045       0   305.7    .016       0
  330.73     .12       0
Bank Sta=289.64,304.75
XS Rating Curve= 0 ,0
Exp/Cntr=0.3,0.1

Type RM Length L Ch R = 1 ,365.4   ,104.3,80.4,56
XS GIS Cut Line= 3
     1745497.398      397490.441     1745846.834      397512.073
     1746029.994      397404.434
#Sta/Elev= 30
       0   894.7    1.25894.0094       8  891.12    35.8  883.29    47.7   883.7
    79.6  879.27   103.4  877.67   107.4  876.86   119.4  871.92   127.3  870.44
   208.4867.1475  267.58864.2673  297.17863.4768     309  861.17   314.3  860.63
     324   861.6  326.27862.1445  326.76 862.316   334.2  864.52     354  864.84
  357.34865.7251   361.9  869.12   373.7  882.09   377.6  885.46   389.4  894.51
   401.2  902.02   440.6  924.89   468.1  938.71   503.5   959.9   562.6  988.52
#Mann= 10 ,-1 , 0
       0    .016       0    1.25     .12       0   208.4     .06       0
  267.58     .12       0  297.17    .016       0     309    .045       0
     324    .016       0  326.27     .12       0  326.76    .016       0
  357.34     .12       0
Bank Sta=309,324
XS Rating Curve= 0 ,0
Exp/Cntr=0.3,0.1

Type RM Length L Ch R = 1 ,285     ,108,104.4,101
XS GIS Cut Line= 3
     1745625.064      397716.884     1745746.592      397681.293
     1746038.674      397407.038
#Sta/Elev= 30
       0  900.22    11.9  896.04   22.16889.5651    27.7   886.6    31.7  885.66
    51.4  883.63    71.2  875.88   83.71872.5975      95  869.98   110.8  868.21
  151.16866.5829  160.25866.3747   209.9  863.58  246.55862.8725   265.5  862.26
   274.4  860.58   281.3  859.52   289.4  861.25   289.7861.3423   301.2  864.07
   313.1     864     317  864.72     321  867.89  332.85880.4808   344.8  890.54
   360.7  899.84   368.6  905.36   451.9  953.24   471.8  963.76   527.3  990.08
#Mann= 10 ,-1 , 0
       0     .12       0   22.16    .016       0   83.71     .06       0
  151.16     .08       0  160.25     .06       0  246.55     .12       0
   274.4    .045       0   289.4     .12       0   289.7    .016       0
  332.85     .12       0
Bank Sta=274.4,289.4
XS Rating Curve= 0 ,0
Exp/Cntr=0.3,0.1

Type RM Length L Ch R = 1 ,180.6   ,51.5,51.6,51.6
XS GIS Cut Line= 4
     1745622.337       397746.12     1745828.605      397782.906
     1745958.967      397615.298     1746046.487      397425.267
#Sta/Elev= 30
       0  904.57     7.9   900.2    35.6  892.66   54.37884.8643    63.2  881.85
   84.37876.7586    98.8  874.79  144.38871.4088  172.58869.8044  204.38868.8174
  249.38867.4354  255.16867.1145  297.49863.3445  329.99862.0709   345.6 861.616
   358.9  861.53  367.41860.1205   368.5   859.8   374.7   858.2   383.5  859.68
  393.71863.3335   410.1  862.67   417.9  864.48   421.9  866.83   433.7  876.46
  439.58879.9185   512.6  921.41   567.9  954.55   591.6  966.57   631.1  983.48
#Mann= 16 ,-1 , 0
       0     .12       0   54.37     .06       0   84.37    .016       0
  144.38     .06       0  172.58    .016       0  204.38     .06       0
  249.38    .016       0  255.16     .06       0  297.49    .016       0
  329.99     .12       0   345.6    .016       0  367.41     .12       0
   368.5    .045       0   383.5     .12       0  393.71    .016       0
  439.58     .12       0
#XS Ineff= 2 , 0
                          405.26          864.59
Permanent Ineff=
       F       F
Bank Sta=368.5,383.5
XS Rating Curve= 0 ,0
Exp/Cntr=0.3,0.1

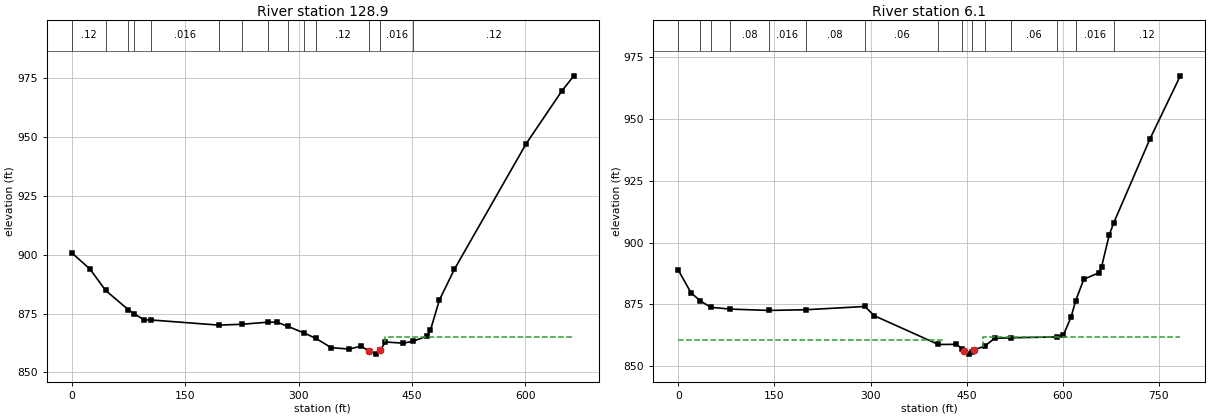
Type RM Length L Ch R = 1 ,128.9   ,120.8,122.8,124.8
XS GIS Cut Line= 4
     1745631.869      397761.626      1745875.48      397806.344
     1746004.907      397639.938     1746072.824      397445.991
#Sta/Elev= 30
       0   900.8      24  893.94   44.73884.8287   74.76876.6335   81.95874.9813
    95.9  872.29  104.79872.2556  194.88870.0592  224.91870.4324   259.3  871.31
   271.6  871.31  285.59869.5488  307.41866.6989  323.01864.3907   343.1  860.48
     367  859.88   382.9  861.15     393  858.94   402.8  857.73     408  859.28
   414.7  862.89   438.6  862.39  451.73863.2769   470.4  865.42   474.3  867.88
   486.2  880.74   505.9  893.75   600.8  947.13   648.2  969.68     664  976.08
#Mann= 14 ,-1 , 0
       0     .12       0   44.73     .06       0   74.76    .016       0
   81.95     .12       0  104.79    .016       0  194.88     .06       0
  224.91    .016       0   259.3     .06       0  285.59    .016       0
  307.41     .06       0  323.01     .12       0     393    .045       0
     408    .016       0  451.73     .12       0
#XS Ineff= 2 , 0
                          414.65          864.83
Permanent Ineff=
       F       F
Bank Sta=393,408
XS Rating Curve= 0 ,0
Exp/Cntr=0.3,0.1

Type RM Length L Ch R = 1 ,6.1     ,8.3,6.1,3.9
XS GIS Cut Line= 4
     1745655.284      397799.719     1745975.758      397858.377
     1746138.953      397683.029     1746118.988      397466.015
#Sta/Elev= 30
       0  888.92    19.9  879.72   34.65876.3945   50.95873.8633   80.98873.1414
  141.03872.5996  198.68 872.879  291.16 874.189   305.9  870.46  405.84858.8568
   433.6  858.93   442.9   857.2   445.6  856.28   453.6  854.97   457.9  855.83
   461.5  856.76  478.11858.1434   493.5  861.37  518.46861.5526   590.2 861.911
     601  862.73   612.9  869.92  619.86876.3676   632.7  885.18   656.5   887.8
   660.4  890.14   672.3  902.98  679.18907.7857   735.7  941.66   783.3  967.26
#Mann= 15 ,-1 , 0
       0     .12       0   34.65     .06       0   50.95     .12       0
   80.98     .08       0  141.03    .016       0  198.68     .08       0
  291.16     .06       0  405.84     .12       0   442.9    .045       0
   457.9     .12       0  478.11    .016       0  518.46     .06       0
   590.2     .12       0  619.86    .016       0  679.18     .12       0
#XS Ineff= 2 , 0
          411.97  860.81  474.72          861.76
Permanent Ineff=
       F       F
Bank Sta=445.6,461.5
XS Rating Curve= 0 ,0
Exp/Cntr=0.3,0.1

Chan Stop Cuts=-1
Use User Specified Reach Order=0
Composite Channel Slope=5